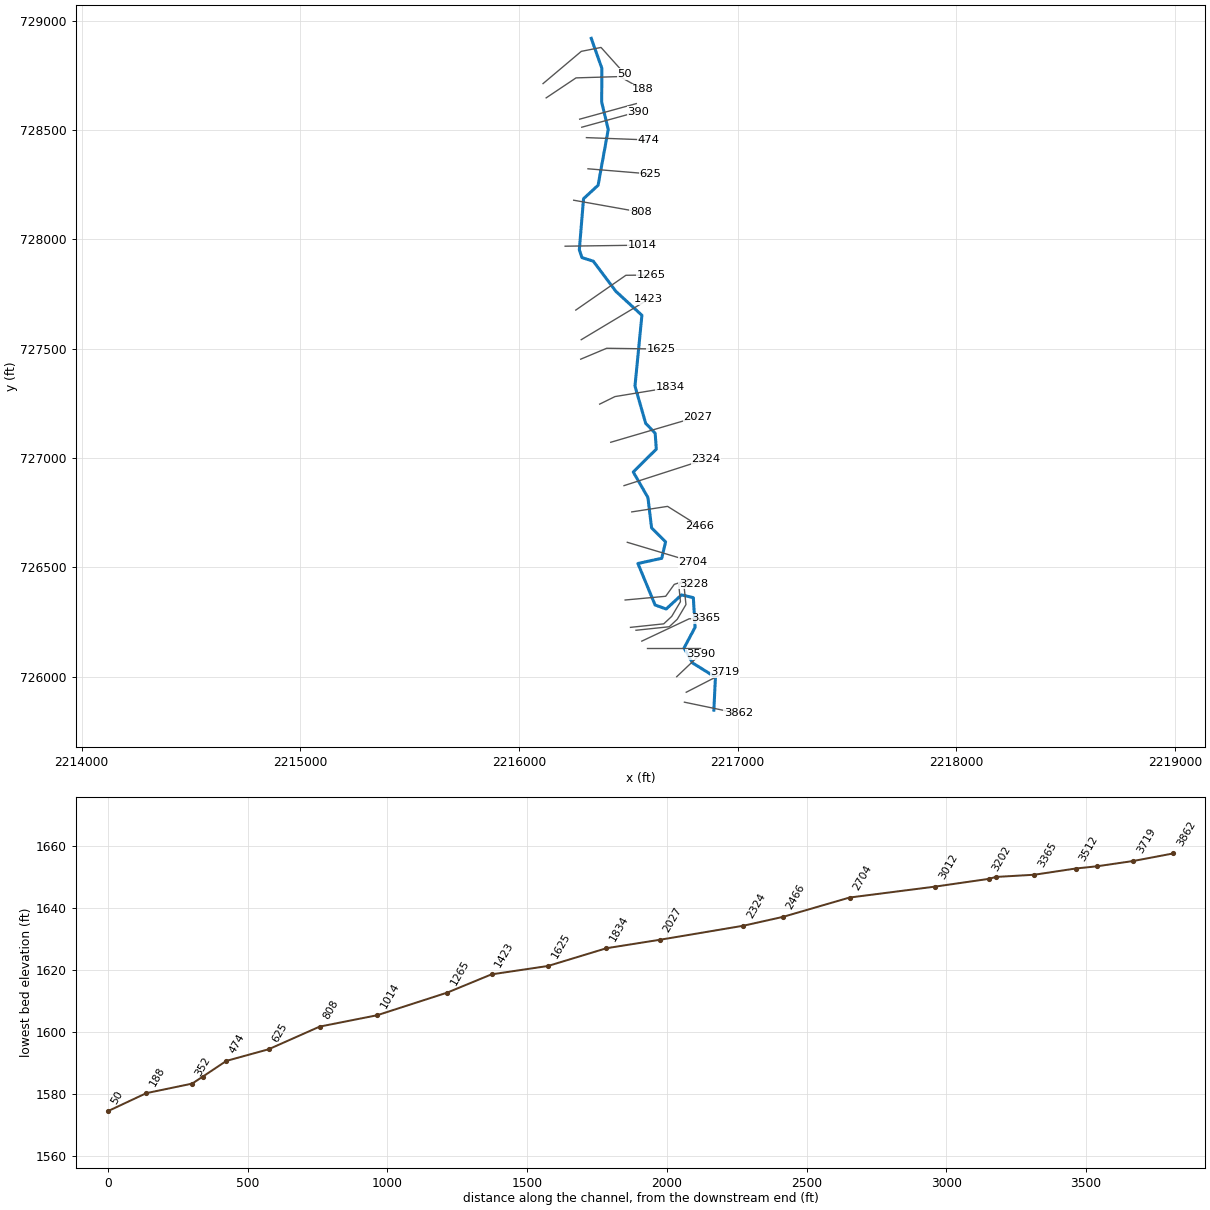
--- MFLAURELRN.prj (project) ---

Proj Title=MFLAURELRN
Current Plan=p01
Default Exp/Contr=0,0
English Units
Geom File=g01
Flow File=f01
Plan File=p01
BEGIN DESCRIPTION:
---------- MODELED AS PART OF WVEMD CTP PROGRAM, 2023----------
Stream Name: MFLAURELRN
Flood Zone:  AFH
Upshur County, WV
HEC-RAS Version: RAS 6.3
Vertical Datum: NAVD88
Projection: NAD 1983 StatePlane West Virginia S FIPS 4702 (US Feet)
Terrain: 1-meter LIDAR (FEMA Region III 3DEP collected 2016-2018)
Land Use: 2019 NLCD
Hydrologic Method:
WV 2010 Regional Regression Equations
Additional Model Notes:
Main stem is LAUFSANDRN
END DESCRIPTION:
DSS Export Rating Curves= 0
DSS Export Rating Curve Sorted= 0
DSS Export Volume Flow Curves= 0
DXF OffsetX= 0
DXF OffsetY= 0
DXF ScaleX= 0
DXF ScaleY= 0

--- MFLAURELRN.p01 (plan) ---

Plan Title=Floodplain
Program Version=6.31
Short Identifier=Floodplain
Geom File=g01
Flow File=f01
Subcritical Flow
K Sum by GR= 0
Std Step Tol= 0.01
Critical Tol= 0.01
Num of Std Step Trials= 20
Max Error Tol= 0.3
Flow Tol Ratio= 0.001
Split Flow NTrial= 30
Split Flow Tol= 0.02
Split Flow Ratio= 0.02
Log Output Level= 0
Friction Slope Method= 1
Unsteady Friction Slope Method= 2
Unsteady Bridges Friction Slope Method= 1
Parabolic Critical Depth
Global Vel Dist= 0 , 0 , 0
Global Log Level= 0
CheckData=True
Encroach Param=-1 ,0,0, 0
Mapping Interval=1HOUR
Computation Time Step Use Courant=        0
Computation Time Step Use Time Series=    0
Computation Time Step Count To Double=0
Computation Time Step Max Doubling=0
Computation Time Step Max Halving=0
Computation Time Step Residence Courant=0
Run HTab= 0
Run UNet= 0
Run Sediment= 0
Run PostProcess= 0
Run WQNet= 0
Run RASMapper=-1
UNET Theta= 0
UNET Theta Warmup= 0
UNET ZTol= 0
UNET ZSATol= 0
UNET MxIter= 0
UNET Max Iter WO Improvement= 0
UNET MaxInSteps= 0
UNET DtIC= 0
UNET DtMin= 0
UNET MaxCRTS= 0
UNET WFStab= 0
UNET SFStab= 0
UNET WFX= 1
UNET SFX= 1
UNET Gravity=32.17405
UNET 1D Methodology=Finite Difference
UNET DSS MLevel= 1
UNET Pardiso=0
UNET DZMax Abort= 0
UNET Use Existing IB Tables= 0
UNET Froude Reduction=False
UNET Froude Limit= 0
UNET Froude Power= 0
UNET D1 Cores= 0
UNET WindReference=Eulerian
UNET WindDragFormulation=Hsu (1988)
UNET D2 Coriolis=0
UNET D2 Cores= 0
UNET D2 Theta= 1
UNET D2 Theta Warmup= 1
UNET D2 Z Tol= 0.01
UNET D2 Volume Tol= 0.01
UNET D2 Max Iterations= 20
UNET D2 Equation= 0
UNET D2 RampUpFraction=0.1
UNET D2 TimeSlices= 1
UNET D2 Turbulence Formulation=Non-Conservative (original)
UNET D2 Eddy Viscosity=0.3
UNET D2 Transverse Eddy Viscosity=0.1
UNET D2 Smagorinsky Mixing=0
UNET D2 BCVolumeCheck=0
UNET D2 Cores=0
UNET D2 SolverType=PARDISO (Direct)
UNET D2 Minimum Iterations= 3
UNET D2 Maximum Iterations= 30
UNET D2 Restart Number= 10
UNET D2 Relaxation Coeff=1.3
UNET D2 SOR Precondition Iterations= 10
UNET D2 ILUT Maximum Fill= 8
UNET D2 ILUT Tolerance=1E-08
UNET D2 Convergence Tolerance=0.00001
UNET D1D2 MaxIter= 0
UNET D1D2 ZTol=0.01
UNET D1D2 QTol=0.1
UNET D1D2 MinQTol=1
Write IC File= 0
Write IC File at Fixed DateTime=0
Write IC File at Sim End=0
Echo Input=False
Echo Parameters=False
Echo Output=False
Write Detailed= 0
HDF Write Warmup=0
HDF Write Time Slices=0
HDF Flush=0
HDF Compression= 1
HDF Chunk Size= 1
HDF Spatial Parts= 1
HDF Use Max Rows=0
HDF Fixed Rows= 1
Calibration Method= 0
Calibration Iterations= 20
Calibration Max Change=0.05
Calibration Tolerance=0.2
Calibration Maximum=1.5
Calibration Minimum=0.5
Calibration Optimization Method= 1
WQ AD Non Conservative
WQ ULTIMATE=-1
WQ Max Comp Step=1HOUR
WQ Output Interval=15MIN
WQ Output Selected Increments= 0
WQ Create Restart=0
WQ Fixed Restart=0
WQ System Summary=0
WQ Write To DSS=0
Sorting and Armoring Iterations= 10
XS Update Threshold= 0.02
Bed Roughness Predictor= 0
Hydraulics Update Threshold= 0.02
Energy Slope Method= 1
Volume Change Method= 1
Sediment Retention Method= 0
Sediment TS Multiplier= 1
Warm Up Method= 0
XS Weighting Method= 0
Number of US Weighted Cross Sections= 1
Number of DS Weighted Cross Sections= 1
Upstream XS Weight=0
Main XS Weight=1
Downstream XS Weight=0
Number of DS XS's Weighted with US Boundary= 1
Upstream Boundary Weight= 1
Weight of XSs Associated with US Boundary= 0
Number of US XS's Weighted with DS Boundary= 1
Downstream Boundary Weight= 0.5
Weight of XSs Associated with DS Boundary= 0.5
Percentile Method= 0
Sediment Output Level= 3
Mass or Volume Output= 0
Output Increment Type= 1
Profile and TS Output Increment= 1
Transport Output Increment 1
XS Output Flag= 0
XS Output Increment= 10
Read HDF5 Sediment Hotstart= 0
Sediment Hotstart Type= 0
Write Gradation File= 0
Read Gradation Hotstart= 0
Write HDF5 File= 1
Write Binary Output= 1
Write DSS Sediment File= 0
DSS Sediment Output Type= 1
SV Curve= 0
Specific Gage Flag= 0
Subcell Erosion Methods= 0
Subcell Deposition Methods= 0
Advection Scheme= 1
Matrix Solver= 0
Implicit Weighting Factor= 1
Maximum Outer Loop Convergence Iterations= 5
Convergence Maximum Absolute= 0.001
Convergence RMSE= 0.0001
Grain Fractions Max Abs Error= 0.001
Max Subgrid Regions= 1
Max Subgrid Length Scale= 3.402823E+38
Initial Layer Thickness= 3.402823E+38
Min Layer Thickness= 3.402823E+38
Max Layer Thickness= 3.402823E+38
Number of Layers= 5

--- MFLAURELRN.f01 (steady flow) ---

Flow Title=Flows
Program Version=6.31
Number of Profiles= 1
Profile Names=01pct
River Rch & RM=MFLAURELRN,Main,3862
     347
Boundary for River Rch & Prof#=MFLAURELRN,Main            , 1
Up Type= 0
Dn Type= 3
Dn Slope=0.04052
DSS Import GetInterval= 0
DSS Import GetPeak= 0
DSS Import FillOption= 0

--- MFLAURELRN.g01 (geometry) ---

Geom Title=Geometry
Program Version=6.31

River Reach=MFLAURELRN      ,Main
Reach XY= 30
      2216891.16       725847.49       2216898.4      725998.241
     2216794.093      726063.201      2216754.86      726131.651
     2216805.339      726226.486     2216797.298      726361.813
     2216743.299      726374.661     2216673.218      726310.046
     2216622.424      726328.389     2216543.957      726518.115
     2216652.786      726541.981      2216670.47      726617.271
     2216606.398      726681.028     2216589.601      726819.818
     2216522.495      726936.802     2216627.975      727041.051
     2216622.796      727113.7942216579.33432672727159.298377767
      2216530.45      727329.676     2216562.129       727653.27
     2216443.199      727762.613     2216340.066      727900.487
     2216287.812      727917.142     2216275.936      727952.741
     2216295.167      728186.079     2216361.814       728247.89
     2216408.173      728503.034     2216378.154      728627.973
     2216379.041      728782.473     2216330.479      728919.746

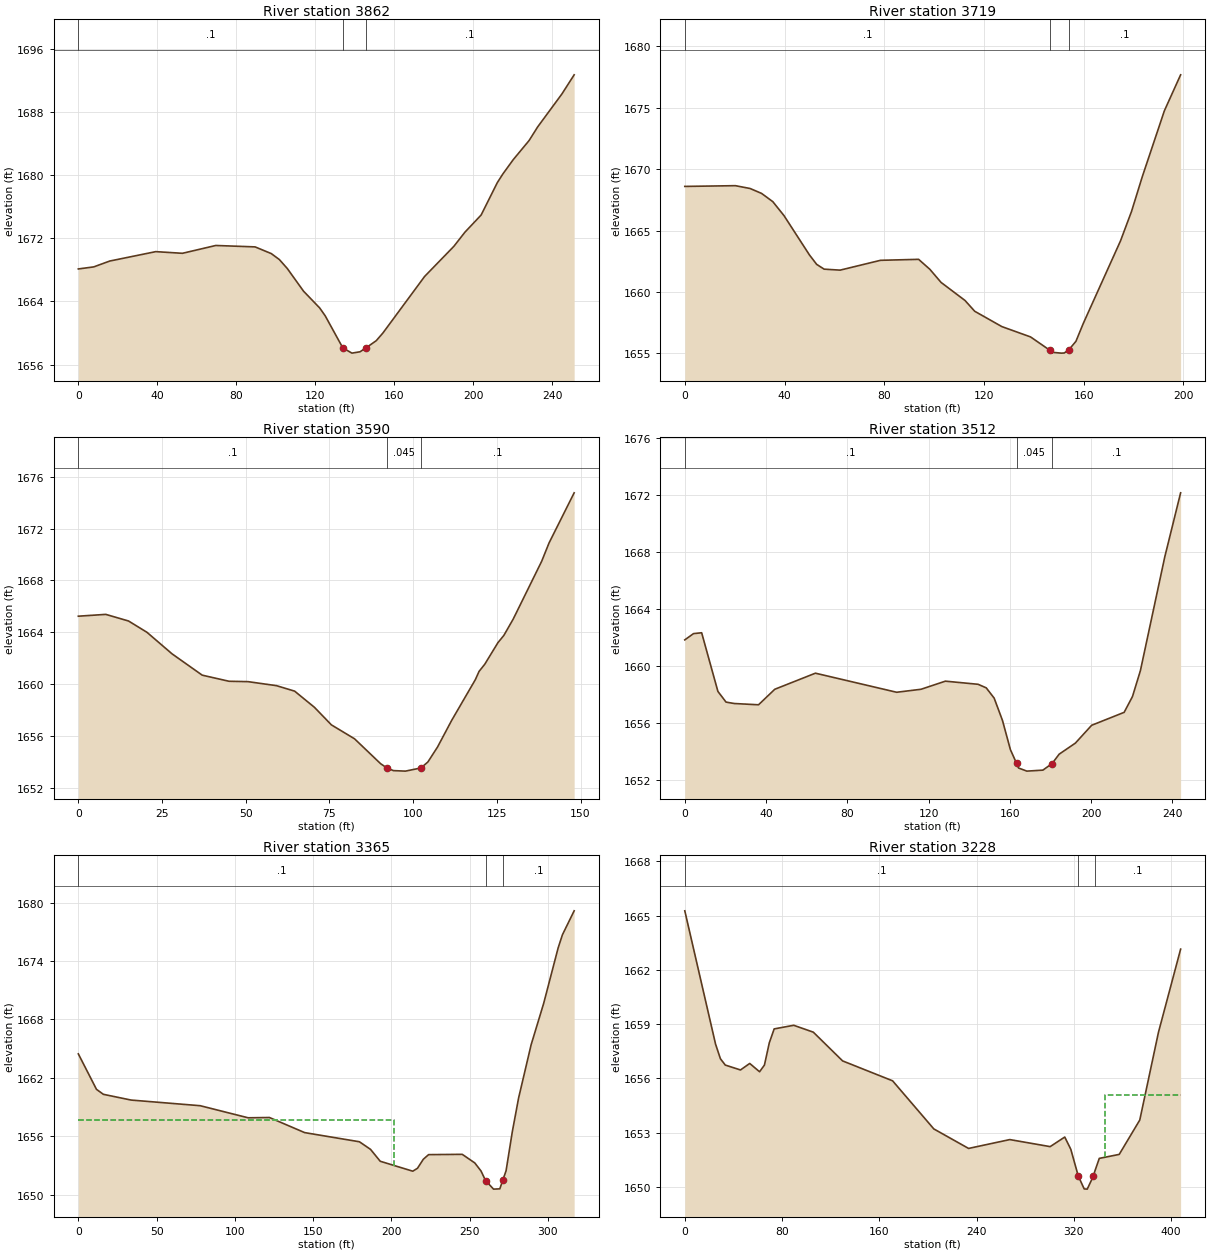
Type RM Length L Ch R = 1 ,3862    ,143.4,143.4,143.4
XS GIS Cut Line= 2
2216756.56080328725883.9518452162217002.29085166725832.758085137
#Sta/Elev= 30
       0 1668.11     7.8 1668.37    15.9 1669.11    39.2  1670.3    52.7 1670.09
    69.6 1671.08    89.5  1670.9    97.7 1670.05   101.8 1669.29   105.8 1668.16
     114  1665.3   122.2 1663.17     125 1662.17   133.9 1658.12   138.5 1657.46
   142.6 1657.63   145.6 1658.12   150.8 1659.03   154.2 1660.01   175.3 1667.16
   190.1 1670.97   195.7 1672.76   203.9 1674.93   212.1 1679.03     215 1680.16
   220.2 1681.95   228.2 1684.36   232.5 1686.07   244.8 1690.25     251 1692.67
#Mann= 3 ,-1,0
       0      .1       0   133.9    .045       0   145.6      .1       0
Bank Sta=133.9,145.6
XS Rating Curve= 0 ,0
Exp/Cntr(USF)=0,0
Exp/Cntr=0.3,0.1

Type RM Length L Ch R = 1 ,3719    ,126.6,129.3,130.8
XS GIS Cut Line= 2
2216764.74943481725929.3231051142216941.71551903726020.176228713
#Sta/Elev= 30
       0  1668.6    20.3 1668.66    26.2 1668.43    30.8 1668.03    35.3 1667.36
    39.8 1666.22      50 1663.02    52.9 1662.25    55.9 1661.86    62.3 1661.78
    78.5 1662.58    93.8 1662.66    98.3 1661.85   102.8 1660.78   112.4 1659.31
   116.3 1658.43   127.2 1657.18   138.7 1656.34  146.39 1655.26   147.7 1655.08
     151 1655.02   152.2 1655.03  153.931655.261   156.9 1655.98   159.9 1657.46
   174.8 1664.17   179.2 1666.56   183.6 1669.44   192.4 1674.77   198.9 1677.69
#Mann= 3 ,-1,0
       0      .1       0  146.39    .045       0  153.93      .1       0
Bank Sta=146.39,153.93
XS Rating Curve= 0 ,0
Exp/Cntr(USF)=0,0
Exp/Cntr=0.3,0.1

Type RM Length L Ch R = 1 ,3590    ,86,77.4,67
XS GIS Cut Line= 2
2216721.29794091726000.4255496692216828.74163491726102.339053532
#Sta/Elev= 30
       0 1665.25     8.2 1665.39      15 1664.88    20.5 1664.01      28 1662.35
      37 1660.71      45 1660.24    50.7 1660.21    59.2  1659.9    64.6 1659.48
    70.5 1658.24    75.6 1656.88    82.5 1655.81    90.3 1653.89    92.2 1653.56
    94.1 1653.36    97.7 1653.32  102.331653.565   104.4 1654.02   107.3 1655.18
   111.5 1657.22   118.6 1660.37   119.7    1661   121.4 1661.55   125.3  1663.2
   127.1 1663.77   129.9 1665.03   138.4 1669.48   140.6 1670.89   148.1 1674.75
#Mann= 3 ,-1,0
       0      .1       0    92.2    .045       0  102.33      .1       0
Bank Sta=92.2,102.33
XS Rating Curve= 0 ,0
Exp/Cntr(USF)=0,0
Exp/Cntr=0.3,0.1

Type RM Length L Ch R = 1 ,3512    ,147.5,147.6,145.1
XS GIS Cut Line= 2
2216583.83321477726133.1501128392216827.95160774726133.150112839
#Sta/Elev= 30
       0 1661.81     4.3 1662.25     8.3 1662.31    16.3 1658.19    20.3 1657.44
    24.3 1657.34    36.3 1657.25    44.3 1658.34    64.3 1659.47   104.3 1658.13
   116.3 1658.34   128.3 1658.91   144.4 1658.69   148.4 1658.44   152.3 1657.72
   156.4 1656.15   160.3  1654.1  163.361653.126   164.3 1652.81   168.4 1652.59
   176.3 1652.66  180.831653.122   184.3 1653.78   192.3 1654.56   200.3 1655.81
   216.3 1656.72   220.4 1657.83   224.3 1659.65   236.3 1667.64   244.1 1672.14
#Mann= 3 ,-1,0
       0      .1       0  163.36    .045       0  180.83      .1       0
Bank Sta=163.36,180.83
XS Rating Curve= 0 ,0
Exp/Cntr(USF)=0,0
Exp/Cntr=0.3,0.1

Type RM Length L Ch R = 1 ,3365    ,118.5,137.4,155.7
XS GIS Cut Line= 3
2216561.71245424726163.1711449852216778.12531659726265.209415794
 2216855.6025584726266.664703171
#Sta/Elev= 30
       0 1664.47    11.6 1660.83      16 1660.32    33.7 1659.73    77.9 1659.15
   108.5 1657.91   122.1 1657.94   144.6 1656.39   179.6 1655.45   186.7 1654.67
   192.9 1653.45   213.7 1652.43   216.7 1652.73   220.4 1653.65   223.8 1654.13
   245.3 1654.16   253.3 1653.28   257.3 1652.45   260.21651.469   265.3 1650.59
   269.3 1650.62   271.31651.552   273.3 1652.47   277.3 1656.49   281.3 1659.94
   289.3  1665.4   297.3 1669.64   306.6 1675.36   309.3 1676.69   316.8 1679.15
#Mann= 3 ,-1,0
       0      .1       0   260.2    .045       0   271.3      .1       0
#XS Ineff= 2 , 0
          201.94 1657.67
Permanent Ineff=
       F       F
Bank Sta=260.2,271.3
XS Rating Curve= 0 ,0
Exp/Cntr(USF)=0,0
Exp/Cntr=0.3,0.1

Type RM Length L Ch R = 1 ,3228    ,26.4,25.8,22.9
XS GIS Cut Line= 6
2216535.05653917726212.8065388822216687.21402252726228.939957477
2216723.79463812726263.1839572172216763.57380109726330.240260516
2216755.48923379726409.1504728272216798.57909083726426.544224871
#Sta/Elev= 30
       0 1665.27    25.3  1657.9    29.3 1657.09    33.3 1656.74    45.8 1656.47
    53.4 1656.83    61.5 1656.37    65.5 1656.74    69.5 1657.97    73.5 1658.74
    89.6 1658.94   105.7 1658.56   129.8 1656.97   170.9 1655.87   204.8 1653.21
   233.4 1652.13   267.3 1652.62   300.5 1652.23   312.5 1652.76   317.5 1652.08
   323.61650.608   328.5 1649.89     331 1649.88  336.03  1650.6   337.31650.883
   340.9 1651.58   357.3  1651.8   374.2  1653.7   389.6 1658.56   407.8 1663.15
#Mann= 3 ,-1,0
       0      .1       0   323.6    .045       0   337.3      .1       0
#XS Ineff= 2 , 0
                          345.63         1655.06
Permanent Ineff=
       F       F
Bank Sta=323.6,336.03
XS Rating Curve= 0 ,0
Exp/Cntr(USF)=0,0
Exp/Cntr=0.3,0.1

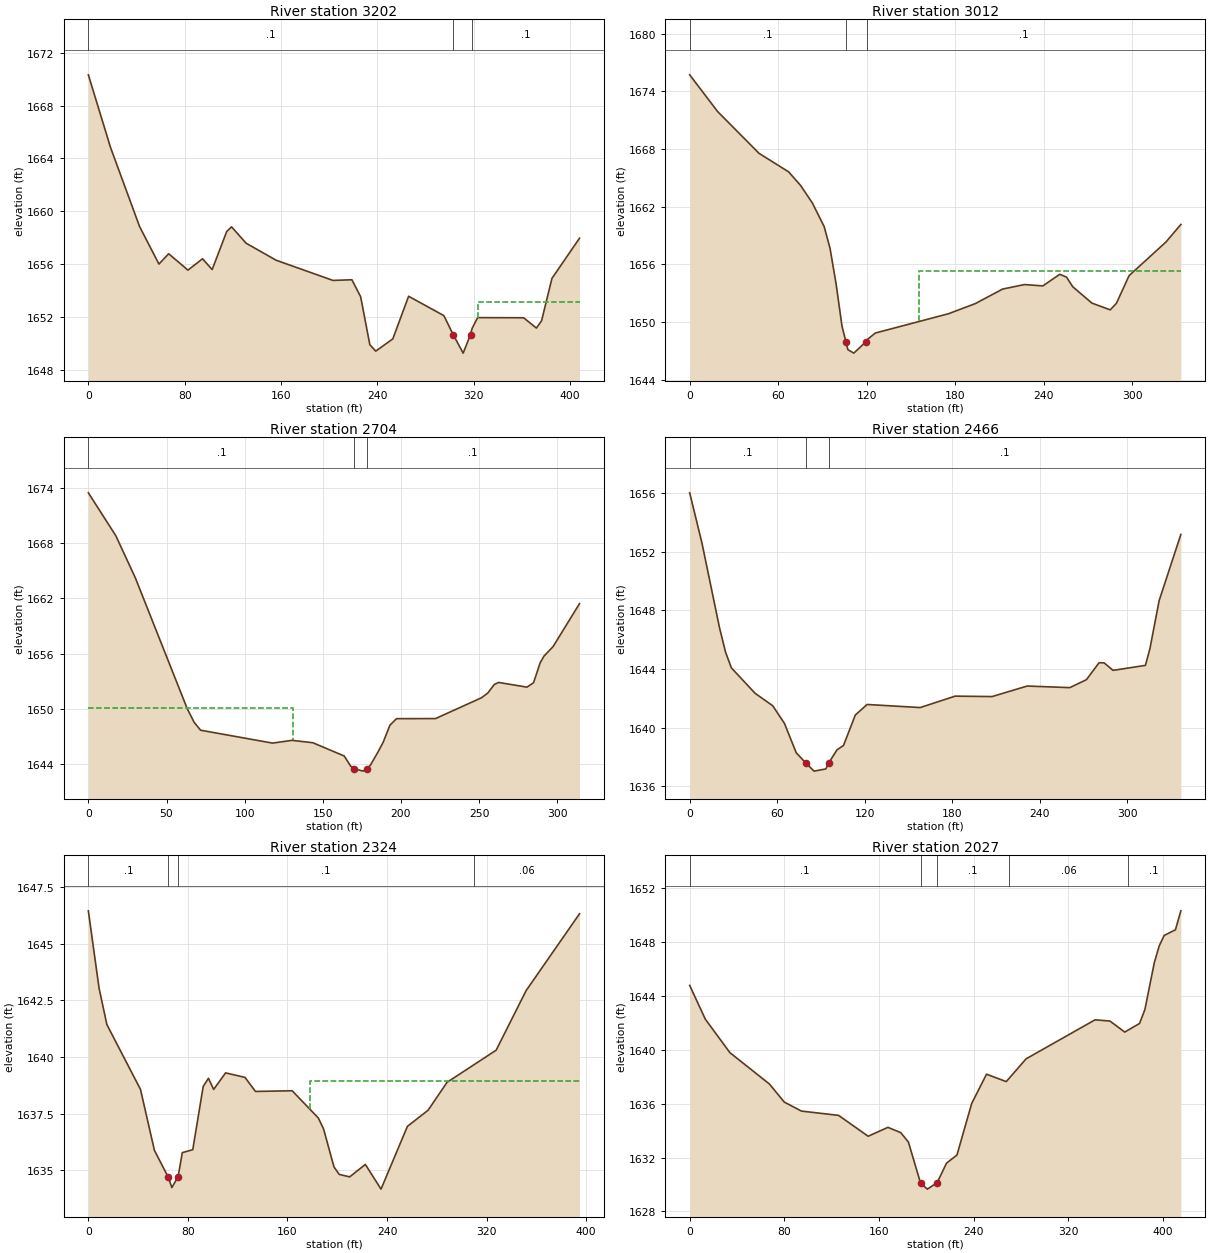
Type RM Length L Ch R = 1 ,3202    ,204.1,190.4,169.9
XS GIS Cut Line= 6
2216509.90304643726226.1091580272216662.06052978726242.242576622
2216698.64114538726276.4865763622216738.42030835726343.542879661
2216730.33574105726422.4530919722216773.42559809726439.846844016
#Sta/Elev= 30
       0 1670.34    18.4 1664.84    42.5 1658.85    58.6    1656    66.7 1656.78
    82.7 1655.54    94.8  1656.4   102.8 1655.58   114.9 1658.47   118.9 1658.82
     131 1657.58   155.9 1656.29   203.1 1654.76   218.8 1654.81   226.1 1653.52
   233.7 1649.89   238.6  1649.4   252.8 1650.33   265.9 1653.56   295.2 1652.09
   302.91650.652   311.2 1649.25  317.31 1650.66   318.6 1651.12   323.2 1651.94
   361.4 1651.93     372 1651.15   376.3  1651.7   384.9 1654.91   407.8 1657.96
#Mann= 3 ,-1,0
       0      .1       0   302.9    .045       0   318.6      .1       0
#XS Ineff= 2 , 0
                          323.28         1653.09
Permanent Ineff=
       F       F
Bank Sta=302.9,317.31
XS Rating Curve= 0 ,0
Exp/Cntr(USF)=0,0
Exp/Cntr=0.3,0.1

Type RM Length L Ch R = 1 ,3012    ,309.8,307.5,299.7
XS GIS Cut Line= 4
2216485.32935345726351.1966284652216670.90288549726368.230215166
2216710.00662051726422.532931852 2216785.5396749726448.440156337
#Sta/Elev= 30
       0 1675.72    18.9 1671.91      47 1667.56    67.1 1665.63    75.2 1664.22
    83.2 1662.39    91.2 1659.94    95.2 1657.67    99.3 1653.97   103.3 1649.58
     106 1647.93   107.3 1647.14   111.3 1646.78  119.42 1647.95   120.51648.198
   125.9 1648.87   175.6 1650.88   193.7 1651.93   212.2 1653.44     227 1653.91
   239.5 1653.77     251 1654.98   255.6 1654.68   259.8 1653.68   272.8 1651.98
   285.2 1651.28   289.4 1651.96     298 1654.84   323.1 1658.35   333.1 1660.16
#Mann= 3 ,-1,0
       0      .1       0     106    .045       0   120.5      .1       0
#XS Ineff= 2 , 0
                          155.85         1655.32
Permanent Ineff=
       F       F
Bank Sta=106,119.42
XS Rating Curve= 0 ,0
Exp/Cntr(USF)=0,0
Exp/Cntr=0.3,0.1

Type RM Length L Ch R = 1 ,2704    ,231.5,237.4,237.2
XS GIS Cut Line= 2
2216495.35017266726615.0666814922216796.35052128726525.003585055
#Sta/Elev= 30
       0 1673.43    17.6 1668.77    30.1 1664.19    63.2 1650.04    67.7 1648.53
    71.8 1647.68   117.8 1646.28   130.3 1646.58   143.6 1646.32   163.7 1644.88
   167.9 1643.76   170.21643.506   175.7 1643.24  178.061643.516   180.4 1643.88
   185.4 1645.35   188.6 1646.37   192.9 1648.22   197.1 1648.93   222.1 1648.94
   251.4 1651.19   255.5 1651.71   259.7 1652.64   262.5 1652.86   280.6 1652.35
   284.8 1652.83     289 1654.98   291.4  1655.7   297.3 1656.75   314.2 1661.41
#Mann= 3 ,-1,0
       0      .1       0   170.2    .045       0  178.06      .1       0
#XS Ineff= 2 , 0
          130.77 1650.08
Permanent Ineff=
       F       F
Bank Sta=170.2,178.06
XS Rating Curve= 0 ,0
Exp/Cntr(USF)=0,0
Exp/Cntr=0.3,0.1

Type RM Length L Ch R = 1 ,2466    ,139.8,142,144.8
XS GIS Cut Line= 3
2216515.89087886726754.1114619552216679.42650134 726779.39233113
 2216824.7914991726688.539207532
#Sta/Elev= 30
       0 1656.03     8.4 1652.61    20.5  1646.8    24.6 1645.15    28.6 1644.08
    44.8 1642.35      57 1641.49      65 1640.29    73.1 1638.28   79.471637.604
    85.3 1637.03    93.4 1637.18   95.35 1637.59   101.1 1638.49   105.5 1638.78
   113.6 1640.86   121.7 1641.58   158.1 1641.37   182.1 1642.15   207.4 1642.12
   231.5 1642.84   260.7 1642.73   272.1 1643.27   280.8 1644.43   284.3 1644.42
   290.4 1643.91   312.6 1644.25   315.7  1645.4     322 1648.67   336.9 1653.19
#Mann= 3 ,-1,0
       0      .1       0   79.47    .045       0   95.35      .1       0
Bank Sta=79.47,95.35
XS Rating Curve= 0 ,0
Exp/Cntr(USF)=0,0
Exp/Cntr=0.3,0.1

Type RM Length L Ch R = 1 ,2324    ,293.3,297.7,297.2
XS GIS Cut Line= 2
2216480.33965659726874.1955905382216856.00074245726995.451339324
#Sta/Elev= 30
       0 1646.45     8.6 1643.04    14.9 1641.43    41.9 1638.57    53.1 1635.88
   64.221634.697    67.1 1634.24    72.1 1634.71    75.5 1635.78    83.9 1635.91
    92.3  1638.7    96.5 1639.06   100.7 1638.57   110.3  1639.3   125.9  1639.1
   134.3 1638.48   163.8 1638.51   184.8 1637.31     189 1636.83   197.4 1635.15
   201.6 1634.82     210 1634.71   222.6 1635.26   235.2 1634.17   256.4 1636.94
     273 1637.65   288.2 1638.88   327.7  1640.3   351.8 1642.93   394.7 1646.32
#Mann= 4 ,-1,0
       0      .1       0   64.22    .045       0    72.1      .1       0
     310     .06       0
#XS Ineff= 2 , 0
                          178.22         1638.94
Permanent Ineff=
       F       F
Bank Sta=64.22,72.1
XS Rating Curve= 0 ,0
Exp/Cntr(USF)=0,0
Exp/Cntr=0.3,0.1

Type RM Length L Ch R = 1 ,2027    ,192.9,192.4,189.1
XS GIS Cut Line= 2
2216419.50756513727072.4924081312216817.68125464727189.416428066
#Sta/Elev= 30
       0  1644.8    13.2 1642.29      34  1639.8    67.4 1637.47    79.9 1636.13
    94.4 1635.46   125.8 1635.14   150.8 1633.59   167.5 1634.25   178.3 1633.86
   184.8 1633.16  195.051630.115   200.8 1629.66   209.1 1630.14     217 1631.59
   225.8 1632.19   238.3 1636.03   250.8  1638.2   267.5 1637.65   284.2 1639.34
   342.5 1642.24   355.1 1642.15   367.6 1641.33   380.1 1641.97   384.6    1643
   392.6  1646.5   396.7 1647.73   400.9 1648.51   410.4 1648.93     415 1650.34
#Mann= 5 ,-1,0
       0      .1       0  195.05    .045       0   209.1      .1       0
     270     .06       0     370      .1       0
Bank Sta=195.05,209.1
XS Rating Curve= 0 ,0
Exp/Cntr(USF)=0,0
Exp/Cntr=0.3,0.1

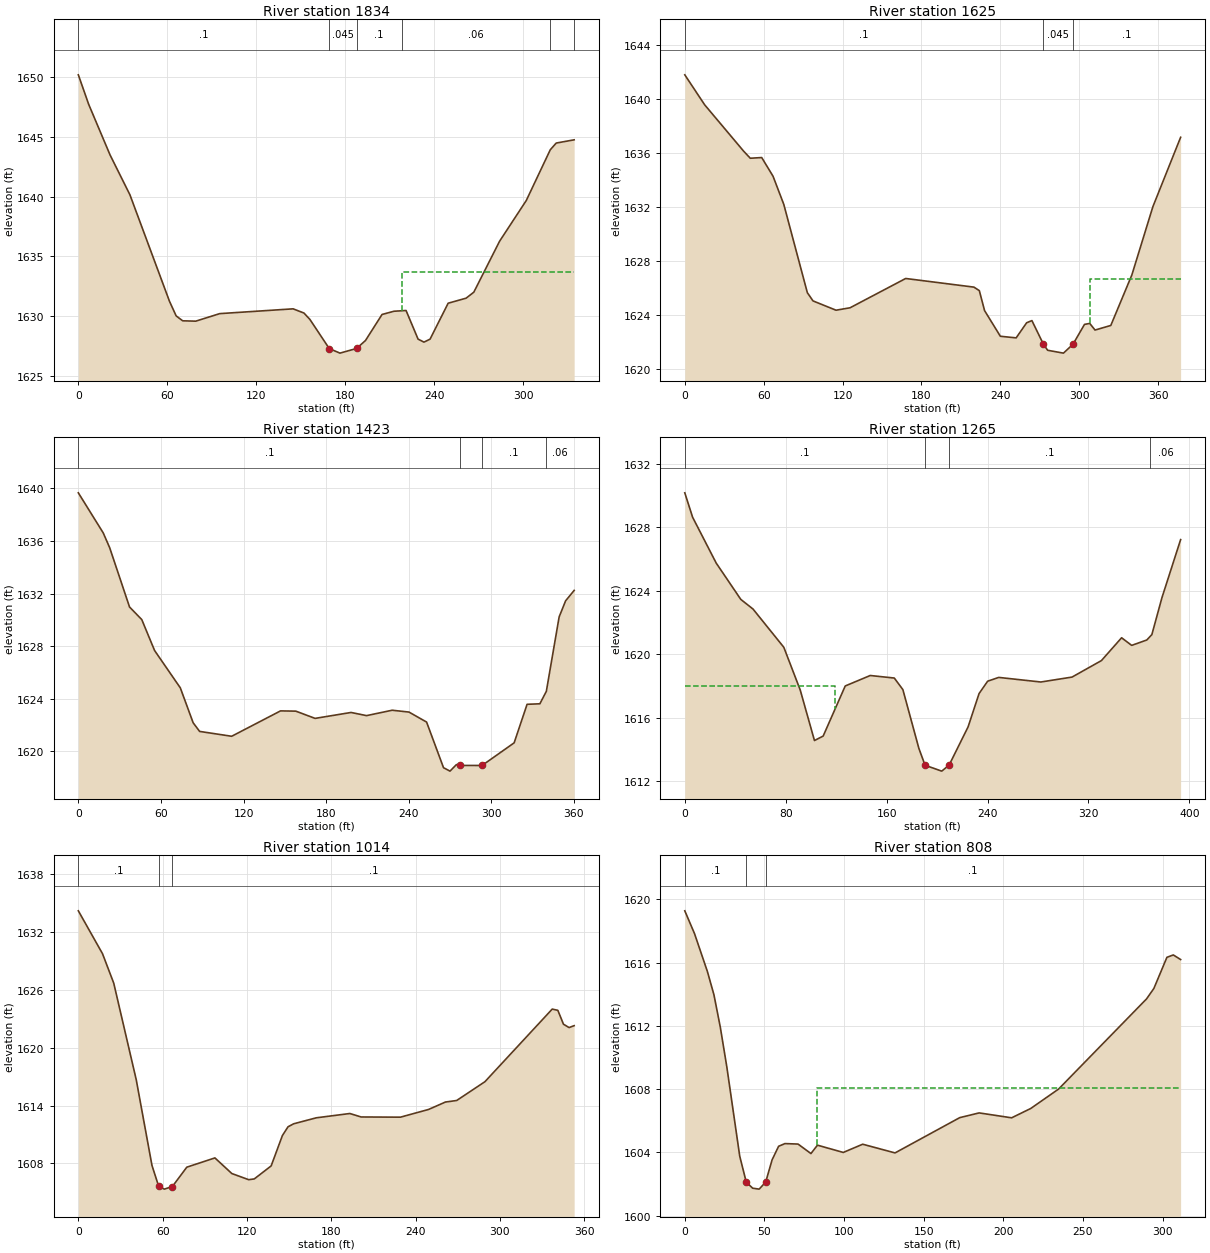
Type RM Length L Ch R = 1 ,1834    ,209.5,209,205.2
XS GIS Cut Line= 3
 2216368.9875723 727247.025014682216439.06812097727281.471386057
2216692.07077971727323.044592892
#Sta/Elev= 30
       0 1650.17       7  1647.7    21.4 1643.48    34.8 1640.15    61.5 1631.25
      66 1630.03    70.4 1629.62    79.2 1629.59    95.4 1630.22   144.9 1630.62
   152.2 1630.27   156.2 1629.74   169.3  1627.3   176.5 1626.92  187.71 1627.31
   193.7 1627.97   204.9 1630.15     213 1630.42   221.1 1630.48   229.2 1628.09
   233.2 1627.84   237.3 1628.09   249.5 1631.09   261.6 1631.51   266.8 1632.01
   284.2 1636.27   302.2 1639.67   318.4 1643.91   322.4 1644.47   334.5 1644.74
#Mann= 6 ,-1,0
       0      .1       0   169.3    .045       0  187.71      .1       0
  218.09     .06       0  318.09      .1       0  334.48     .06       0
#XS Ineff= 1 ,-1
  218.32334.4842  1633.7
Permanent Ineff=
       F
Bank Sta=169.3,187.71
XS Rating Curve= 0 ,0
Exp/Cntr(USF)=0,0
Exp/Cntr=0.3,0.1

Type RM Length L Ch R = 1 ,1625    ,191.7,202.2,207
XS GIS Cut Line= 3
2216282.27774091727452.5154370352216401.05833186727502.403285236
2216649.30976696727498.839867508
#Sta/Elev= 30
       0 1641.82    15.1  1639.6    44.7 1636.17    49.8 1635.64    58.5 1635.69
    67.1 1634.31    75.3 1632.22    93.2 1625.68    97.5 1625.07     115 1624.38
   125.7 1624.56     168 1626.73   219.9 1626.09     224 1625.83     228 1624.35
     240 1622.45     252 1622.33     260 1623.45     264 1623.61   272.8 1621.85
     276 1621.41     288  1621.2  295.251621.859     304 1623.33     308  1623.4
     312 1622.91     324 1623.25     340 1626.99     356 1632.05   377.1 1637.19
#Mann= 3 ,-1,0
       0      .1       0   272.8    .045       0  295.25      .1       0
#XS Ineff= 2 , 0
                          307.97         1626.69
Permanent Ineff=
       F       F
Bank Sta=272.8,295.25
XS Rating Curve= 0 ,0
Exp/Cntr(USF)=0,0
Exp/Cntr=0.3,0.1

Type RM Length L Ch R = 1 ,1423    ,153.9,158.2,154.8
XS GIS Cut Line= 2
2216284.65335272727541.6008802522216593.48288921727726.898602144
#Sta/Elev= 30
       0 1639.66    18.1 1636.61    22.8 1635.48    37.2 1630.98    46.1 1630.02
    55.4 1627.67    74.1 1624.83    83.4 1622.18    88.1 1621.52   111.4 1621.15
   146.9 1623.08     158 1623.06     172 1622.51   198.1 1622.96   209.4 1622.72
     228 1623.13   240.2 1622.99     253 1622.23   265.3 1618.76     270  1618.5
   274.7    1619  277.631618.933   293.3 1618.93   316.6 1620.65     326 1623.58
   335.3 1623.62     340 1624.57   349.3 1630.23     354 1631.45   360.2 1632.24
#Mann= 4 ,-1,0
       0      .1       0  277.63    .045       0   293.3      .1       0
     340     .06       0
Bank Sta=277.63,293.3
XS Rating Curve= 0 ,0
Exp/Cntr(USF)=0,0
Exp/Cntr=0.3,0.1

Type RM Length L Ch R = 1 ,1265    ,255.8,251,245.2
XS GIS Cut Line= 3
2216259.70942862727677.0107539422216488.95596917727836.176745824
2216602.98533649727837.364551734
#Sta/Elev= 30
       0 1630.18     6.2 1628.64    24.9 1625.75    44.4 1623.46    54.1 1622.85
    78.5 1620.44    91.5 1617.75   102.8 1614.56   109.7 1614.84   127.2    1618
     147 1618.66   166.1  1618.5   172.9 1617.77   185.6 1614.06   190.5    1613
   203.7 1612.63  209.551613.009   224.6 1615.42   233.3 1617.52   240.1  1618.3
   248.9 1618.54   282.3 1618.25     307 1618.56   330.3  1619.6   346.3 1621.04
   354.3 1620.56   366.3  1620.9   370.3 1621.24   378.3 1623.57   393.1 1627.23
#Mann= 4 ,-1,0
       0      .1       0   190.5    .045       0  209.55      .1       0
  369.08     .06       0
#XS Ineff= 2 , 0
          119.25 1617.98
Permanent Ineff=
       F       F
Bank Sta=190.5,209.55
XS Rating Curve= 0 ,0
Exp/Cntr(USF)=0,0
Exp/Cntr=0.3,0.1

Type RM Length L Ch R = 1 ,1014    ,207.3,205.6,203.5
XS GIS Cut Line= 2
2216211.00938633727969.2110076952216563.78774147727973.962231334
#Sta/Elev= 30
       0 1634.22    17.2 1629.77    25.2 1626.71    41.2 1616.69    52.4 1607.79
    57.2 1605.61    61.2 1605.33   66.921605.602    77.2 1607.61    97.2 1608.57
   109.2 1606.95   121.2 1606.31   125.2 1606.39   137.2 1607.74   145.2 1610.89
   149.2  1611.8   153.2 1612.11   169.2 1612.73   193.2 1613.18   201.2 1612.82
   229.2  1612.8   249.2  1613.6   261.2 1614.37   269.2 1614.53   289.3 1616.48
   337.2 1624.02   341.2 1623.89   345.2 1622.45   349.2  1622.1   352.8  1622.3
#Mann= 3 ,-1,0
       0      .1       0    57.2    .045       0   66.92      .1       0
Bank Sta=57.2,66.92
XS Rating Curve= 0 ,0
Exp/Cntr(USF)=0,0
Exp/Cntr=0.3,0.1

Type RM Length L Ch R = 1 ,808     ,181.9,182.9,183
XS GIS Cut Line= 2
2216250.20698135728179.4526536882216556.66090602728124.813581848
#Sta/Elev= 30
       0 1619.27     6.1 1617.83    14.2 1615.43    18.3 1613.96    22.3 1611.91
    26.4 1609.39    34.5 1603.75    38.6 1602.11    42.6 1601.73    46.7 1601.67
    50.8 1602.12    54.8 1603.52    58.9 1604.38    62.9 1604.55    71.1 1604.52
    79.2 1603.92    83.3 1604.45    99.5 1603.99   111.7 1604.51     132 1603.96
   172.6 1606.19   184.8 1606.49   205.2 1606.18   217.2 1606.77   234.7    1608
   289.9  1613.7   294.5 1614.36   302.7 1616.33   306.7 1616.48   311.3 1616.19
#Mann= 3 ,-1,0
       0      .1       0    38.6    .045       0    50.8      .1       0
#XS Ineff= 2 , 0
                           83.21         1608.04
Permanent Ineff=
       F       F
Bank Sta=38.6,50.8
XS Rating Curve= 0 ,0
Exp/Cntr(USF)=0,0
Exp/Cntr=0.3,0.1

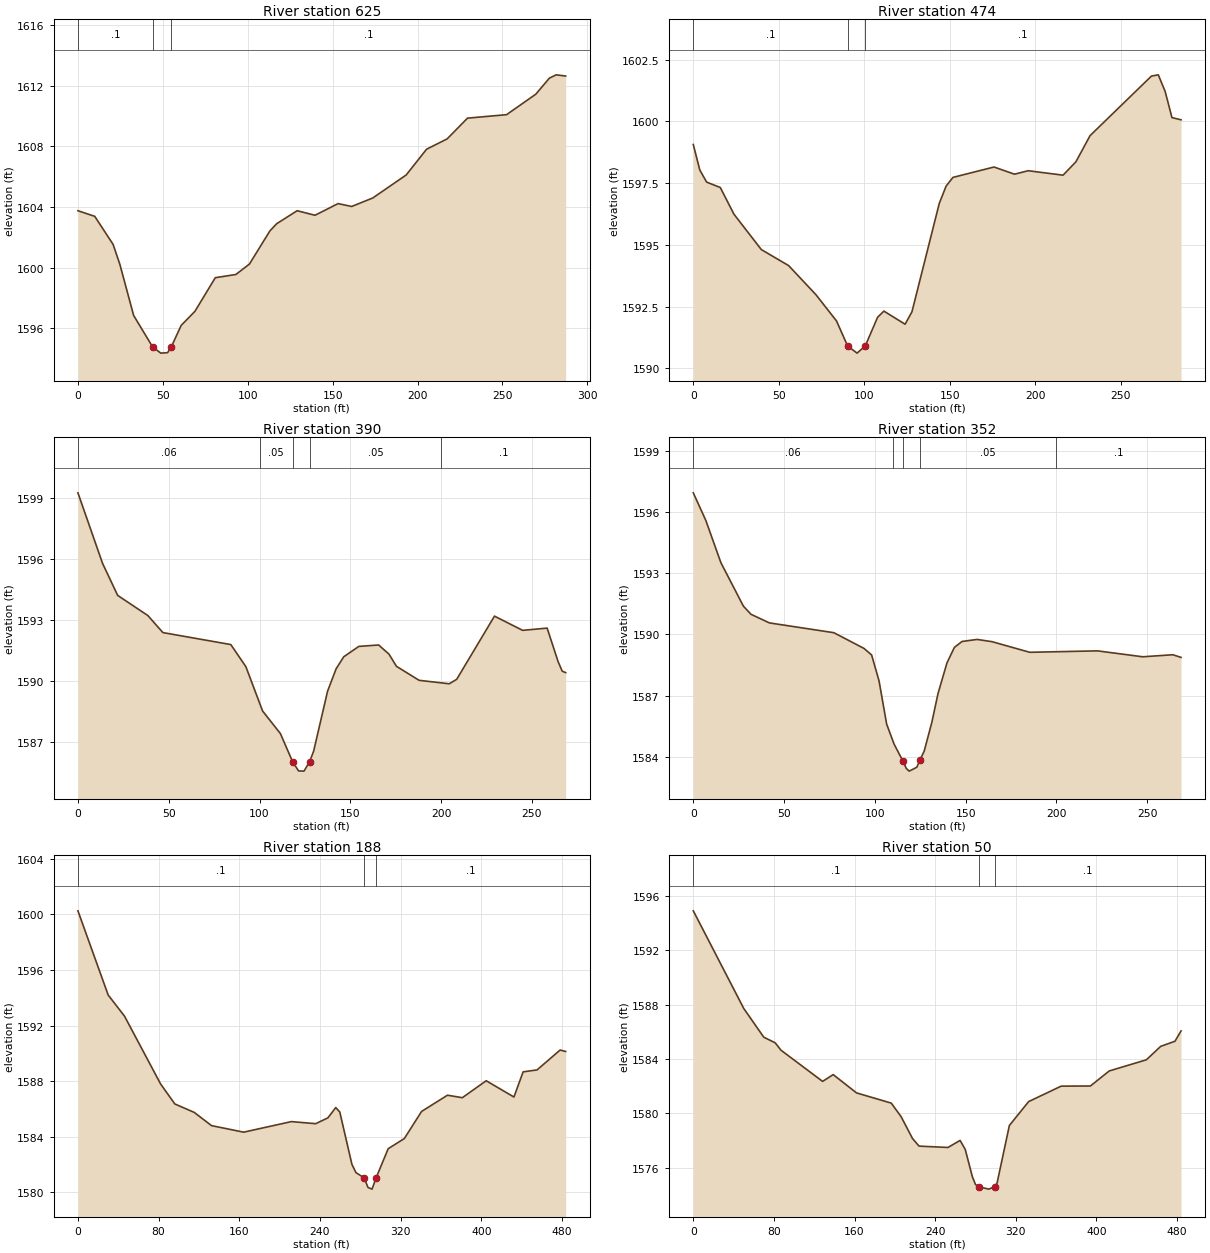
Type RM Length L Ch R = 1 ,625     ,150.7,151,151.3
XS GIS Cut Line= 2
2216315.53630637728323.1771687462216601.79753058728299.421050554
#Sta/Elev= 30
       0 1603.76     9.9 1603.39    20.7 1601.54    24.7 1600.22    32.8 1596.85
   43.961594.774    48.8 1594.36    52.8 1594.39   54.961594.768    60.8 1596.19
    68.9 1597.12    80.9 1599.34      93 1599.55     101 1600.24     113 1602.42
     117  1602.9   129.1 1603.76   139.6 1603.46   153.2 1604.23   161.2 1604.04
   173.6  1604.6   193.3 1606.12   205.3 1607.82   217.4  1608.5   229.4 1609.87
   252.4  1610.1   269.6 1611.45   277.6 1612.51   281.6 1612.73   287.2 1612.65
#Mann= 3 ,-1,0
       0      .1       0   43.96    .045       0   54.96      .1       0
Bank Sta=43.96,54.96
XS Rating Curve= 0 ,0
Exp/Cntr(USF)=0,0
Exp/Cntr=0.3,0.1

Type RM Length L Ch R = 1 ,474     ,81.8,84.4,87.7
XS GIS Cut Line= 2
2216308.40947092728465.7138778942216593.48288921728455.023624707
#Sta/Elev= 30
       0 1599.06     3.8 1598.03     7.8 1597.54    15.8 1597.32    23.8 1596.24
    39.8 1594.81    55.8 1594.16    71.8 1592.98    83.8 1591.92   90.271590.911
    95.8 1590.62  100.621590.913   107.8 1592.07   111.5 1592.32   123.9 1591.79
   127.9 1592.29   143.9 1596.68   147.9 1597.38   151.9 1597.73   175.9 1598.15
   187.9 1597.86   195.9    1598   216.3 1597.82   223.8 1598.36   232.1 1599.42
     268 1601.83     272 1601.88     276 1601.21     280 1600.15   285.3 1600.06
#Mann= 3 ,-1,0
       0      .1       0   90.27    .045       0  100.62      .1       0
Bank Sta=90.27,100.62
XS Rating Curve= 0 ,0
Exp/Cntr(USF)=0,0
Exp/Cntr=0.3,0.1

Type RM Length L Ch R = 1 ,390     ,38.1,38.1,38.1
XS GIS Cut Line= 2
2216287.02896454728513.2261142762216545.97065283 728584.49446885
#Sta/Elev= 30
       0 1599.25    13.6 1595.77    21.9  1594.2    38.5 1593.21    46.8 1592.37
    84.2 1591.78    92.5 1590.69   101.7 1588.51   111.5  1587.4  118.181586.022
   121.5 1585.56   124.5 1585.55   127.6 1586.02   129.8 1586.53   137.5 1589.49
   142.2 1590.59   146.4 1591.18   154.7 1591.69   165.6 1591.76   171.3 1591.31
   175.4 1590.71   187.9 1590.02   204.5 1589.85   208.6 1590.07   229.4 1593.18
   244.9 1592.48   258.4 1592.59   264.4 1590.95   266.7 1590.47   268.6  1590.4
#Mann= 5 ,-1,0
       0     .06       0     100     .05       0  118.18    .045       0
   127.6     .05       0     200      .1       0
Bank Sta=118.18,127.6
XS Rating Curve= 0 ,0
Exp/Cntr(USF)=0,0
Exp/Cntr=0.3,0.1

Type RM Length L Ch R = 1 ,352     ,165.9,163.9,161.3
XS GIS Cut Line= 2
2216277.52651727728550.0480974732216536.46820555728621.316452047
#Sta/Elev= 30
       0 1596.93     6.9 1595.58    15.2 1593.51    27.6 1591.38    31.8 1590.98
    41.9 1590.56    77.4 1590.08      94 1589.31    98.2 1588.99   102.3 1587.72
   106.5  1585.6   110.6 1584.62   115.3 1583.82   117.3 1583.43   118.9  1583.3
   123.1 1583.49  124.721583.822   127.2 1584.29   131.4  1585.7   134.8 1587.11
   139.7  1588.6   143.8 1589.36     148 1589.65   156.3 1589.75   164.5 1589.64
   185.3 1589.12   222.6 1589.19   247.5  1588.9   264.1    1589   268.6 1588.87
#Mann= 5 ,-1,0
       0     .06       0     110     .05       0   115.3    .045       0
  124.72     .05       0     200      .1       0
Bank Sta=115.3,124.72
XS Rating Curve= 0 ,0
Exp/Cntr(USF)=0,0
Exp/Cntr=0.3,0.1

Type RM Length L Ch R = 1 ,188     ,137.8,137.8,137.8
XS GIS Cut Line= 4
2216124.29955493728647.4481820572216260.89723453728738.909237093
2216460.44862734728744.8482666412216564.97554738728686.645777073
#Sta/Elev= 30
       0 1600.26      30  1594.2    46.2 1592.68    81.9 1587.81    96.1 1586.36
   115.4 1585.75   132.5  1584.8   164.4 1584.33   211.7 1585.09   235.8 1584.94
   247.9 1585.36   255.7  1586.1   259.7 1585.78   271.7 1582.02   275.7 1581.42
  283.881581.038   287.7 1580.35   291.7 1580.23   295.7 1581.04   307.7 1583.14
   323.7 1583.87   340.8 1585.82   366.5 1586.99   381.2 1586.81   404.9 1588.03
   432.4 1586.86   441.5 1588.67   455.3 1588.81   478.2 1590.24   483.7 1590.14
#Mann= 3 ,-1,0
       0      .1       0  283.88    .045       0   295.7      .1       0
Bank Sta=283.88,295.7
XS Rating Curve= 0 ,0
Exp/Cntr(USF)=0,0
Exp/Cntr=0.3,0.1

Type RM Length L Ch R = 1 ,50      ,,,
XS GIS Cut Line= 4
2216110.04588402728712.7775070832216284.91008352728860.182408484
2216375.19089214728878.0754373212216484.20474553728756.726325737
#Sta/Elev= 30
       0 1594.92    50.1 1587.72    69.9 1585.61    81.3 1585.19      87 1584.65
   128.3 1582.35   138.8 1582.85     162  1581.5   196.4 1580.75   206.2 1579.75
   217.5 1578.14     224 1577.58   252.7 1577.48   264.7    1578   269.8 1577.34
   276.9 1575.32     280 1574.75  283.31 1574.58   293.2 1574.41  298.86 1574.58
   301.4 1574.86   313.6  1579.1   332.7 1580.86     365    1582     394 1582.01
   412.7 1583.12   449.5 1583.94   463.7 1584.93   477.9 1585.31   483.9 1586.07
#Mann= 3 ,-1,0
       0      .1       0  283.31    .045       0  298.86      .1       0
Bank Sta=283.31,298.86
XS Rating Curve= 0 ,0
Exp/Cntr(USF)=0,0
Exp/Cntr=0.3,0.1
LCMann Table=0

Chan Stop Cuts=-1
Use User Specified Reach Order=0
Composite Channel Slope=5